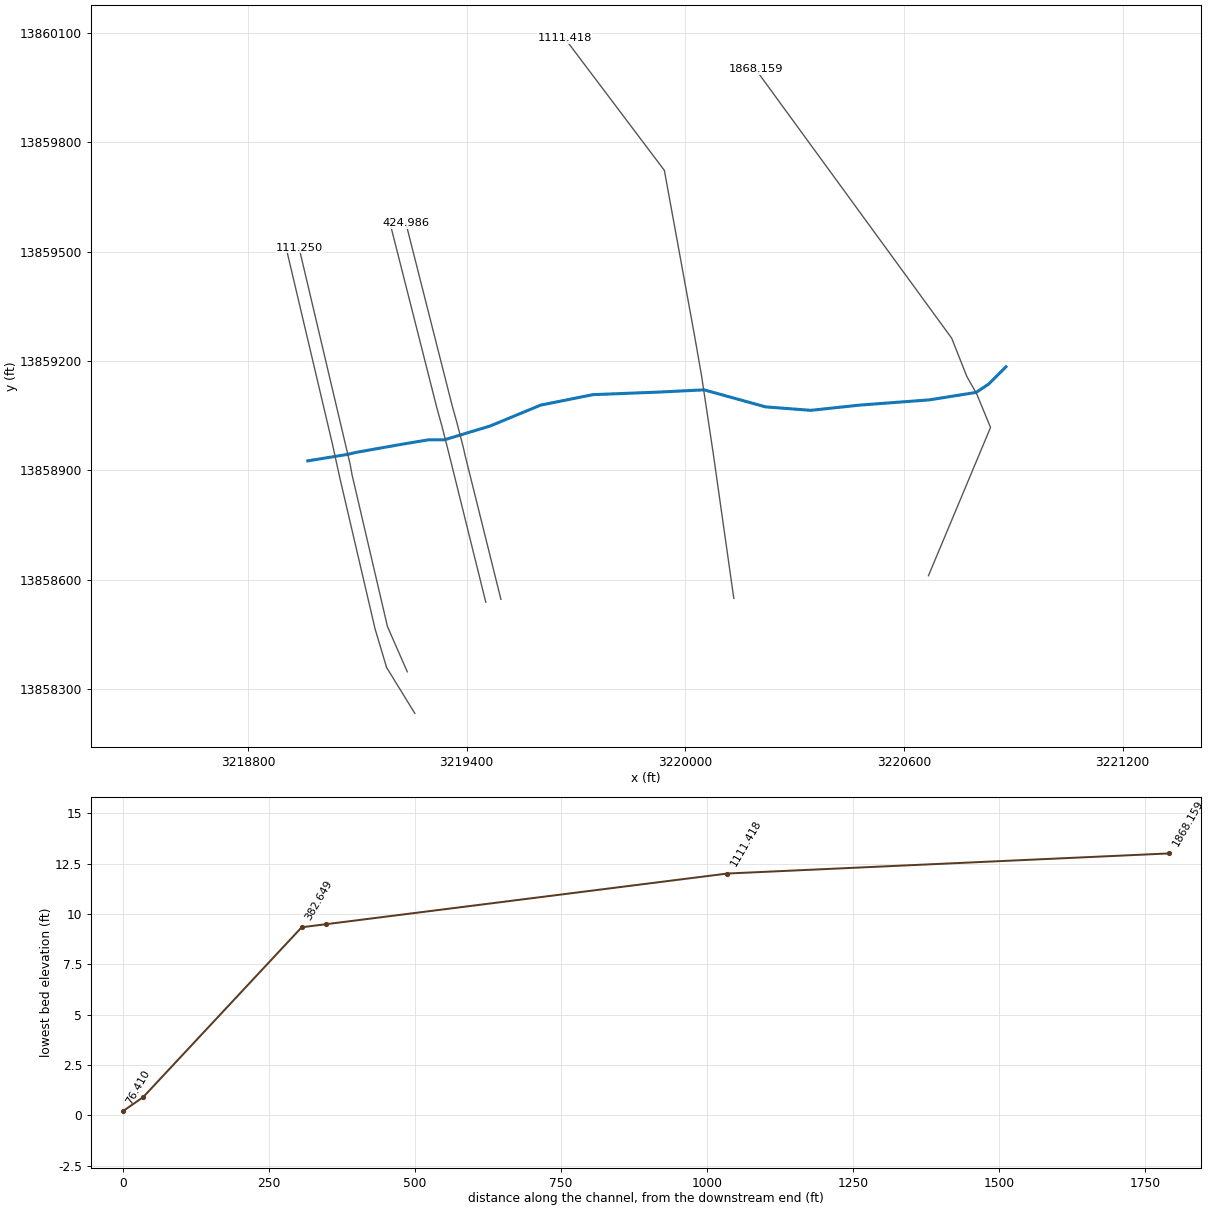
--- O208-00-00.prj (project) ---

Proj Title=O208-00-00
Current Plan=p02
Default Exp/Contr=.3,.1
English Units
Geom File=g04
Flow File=f01
Flow File=f02
Plan File=p01
Plan File=p02
Y Axis Title=Elevation
X Axis Title(PF)=Main Channel Distance
X Axis Title(XS)=Station
BEGIN DESCRIPTION:
Goose Creek Watershed
Spring Gully Diversion Channel
HCFCD Unit O208-00-00
Flood Hazard Model
10, 2, 1, 0.2% Event
Filename O2080000.prj
Prepared By:  FTN	DATE:  January 2004
Reviewed By:	DATE:
STATUS (FINAL RAS)
Normal depth calculated between sections 382.649 and 111.25 with channel inverts of 9.34 and 0.9 respectively. Distance between the sections is 271.4. Normal depth calculated to be 0.0311
Manning's n data adapted from HEC-2 data. flows and flow change locations obtained from hydrology partner (DEC)
END DESCRIPTION:
DSS Export Rating Curves= 0
DSS Export Rating Curve Sorted= 0
DSS Export Volume Flow Curves= 0
DXF OffsetX= 0
DXF OffsetY= 0
DXF ScaleX= 1
DXF ScaleY= 10

--- O208-00-00.p02 (plan) ---

Plan Title=Floodway
Version=Version 3.0.1  Mar 2001
Short Identifier=Floodway0607
Geom File=g04
Flow File=f02
Subcritical Flow
K Sum by GR= 0
Std Step Tol= 0.01
Critical Tol= 0.01
Num of Std Step Trials= 20
Max Error Tol= 0.3
Flow Tol Ratio= 0.001
Split Flow NTrial= 30
Split Flow Tol= 0.02
Split Flow Ratio= 0.02
Log Output Level= 0
Friction Slope Method= 1
Unsteady Friction Slope Method= 2
Parabolic Critical Depth
Global Vel Dist= 0 , 0 , 0
Global Log Level= 0
CheckData=True
Encroach Param=-1 ,0,0, 2
Encroach River=O208-00-00
Encroach Reach=Spr Gully DC
Encroach Node=1868.159
       1  493.11  607.46
Encroach Node=1111.418
       1  509.57  636.82
Encroach Node=424.986
       1   395.8  536.82
Encroach Node=410
       1   395.8  536.82
Encroach Node=382.649
       1  547.08   688.1
Encroach Node=247
       1  501.63   716.7
Encroach Node=111.250
       1  501.63   716.7
Encroach Node=76.410
       1  712.49  770.57
Encroach Reach=O208-00-00_0001
Encroach Node=1868.159
       1  493.11  607.46
Encroach Node=1111.418
       1  509.57  636.82
Encroach Node=424.986
       1   395.8  536.82
Encroach Node=410
       1   395.8  536.82
Encroach Node=382.649
       1  547.08   688.1
Encroach Node=247
       1  501.63   716.7
Encroach Node=111.250
       1  501.63   716.7
Encroach Node=76.410
       1  712.49  770.57
Computation Interval=1HOUR
Output Interval=1HOUR
Run HTab= 0
Run UNet= 0
Run PostProcess= 0
UNET Theta= 1
UNET ZTol= 0.02
UNET ZSATol= 0.1
UNET MxIter= 20
UNET MaxInSteps= 20
UNET DtIC= 0
UNET DtMin= 0
UNET MaxCRTS= 20
UNET WFStab= 2
UNET SFStab= 1
UNET WFX= 1
UNET SFX= 1
UNET Convert EG Bridges=-1
UNET Use Existing IB Tables=-1
Instantaneous Interval=1HOUR
Write IC File= 0
Write Velocity= 0
Write Detailed= 0

--- O208-00-00.p01 (plan) ---

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Plan Title=FEMA Effective June 2007
Short Identifier=FEMAeff0607
Geom File=g04
Flow File=f01
Encroach Param=-1 ,0,0, 0

--- O208-00-00.f02 (steady flow) ---

Flow Title=Floodway
Version=Version 3.0.1  Mar 2001
Number of Profiles= 2
Profile Names=1PCT_100yr, 1PCTFloodway_100yrFW
River Rch & RM=O208-00-00,O208-00-00_0001,1868.159
     951     951
Boundary for River Rch & Prof#=O208-00-00,O208-00-00_0001, 1
Up Type= 0
Dn Type= 3
Dn Slope=.0311
Boundary for River Rch & Prof#=O208-00-00,O208-00-00_0001, 2
Up Type= 0
Dn Type= 3
Dn Slope=.0311
DSS Import GetInterval= 0
DSS Import GetPeak= 0
DSS Import FillOption= 0

--- O208-00-00.f01 (steady flow) ---

Flow Title=FEMA Effective June 2007
Version=Version 3.0.1  Mar 2001
Number of Profiles= 4
Profile Names=10PCT_10yr, 2PCT_50yr, 1PCT_100yr, 0.2PCT_500yr
River Rch & RM=O208-00-00,O208-00-00_0001,1868.159
     440     758     951    1559
Boundary for River Rch & Prof#=O208-00-00,O208-00-00_0001, 1
Up Type= 0
Dn Type= 3
Dn Slope=.0311
Boundary for River Rch & Prof#=O208-00-00,O208-00-00_0001, 2
Up Type= 0
Dn Type= 3
Dn Slope=.0311
Boundary for River Rch & Prof#=O208-00-00,O208-00-00_0001, 3
Up Type= 0
Dn Type= 3
Dn Slope=.0311
Boundary for River Rch & Prof#=O208-00-00,O208-00-00_0001, 4
Up Type= 0
Dn Type= 3
Dn Slope=.0311
DSS Import GetInterval= 0
DSS Import GetPeak= 0
DSS Import FillOption= 0

--- O208-00-00.g04 (geometry) ---

Geom Title=O208-00-00 June 2007
Version=Version 3.0.1  Mar 2001

River Reach=O208-00-00      ,O208-00-00_0001
Reach XY= 30
     3220880.066    13859184.529     3220832.244    13859136.708
     3220810.141    13859122.198     3220797.782    13859114.086
     3220669.653    13859093.669     3220562.165    13859085.608
     3220509.991    13859081.694     3220478.368    13859079.323
     3220413.984    13859072.424     3220365.667    13859067.248
     3220344.469    13859064.976     3220220.134    13859074.541
     3220051.746    13859121.178     3219925.412    13859114.972
     3219813.984    13859110.634     3219786.344    13859109.559
     3219746.704    13859108.015     3219603.241    13859079.323
      3219464.56    13859021.937     3219372.108    13858994.074
     3219338.984     13858984.09     3219295.095     13858984.09
     3219273.984    13858980.541     3219258.984    13858978.018
     3219231.321    13858973.367     3219228.739    13858972.932
     3219214.409    13858970.523     3219098.287    13858949.863
     3219073.168    13858944.066     3218964.226    13858926.293

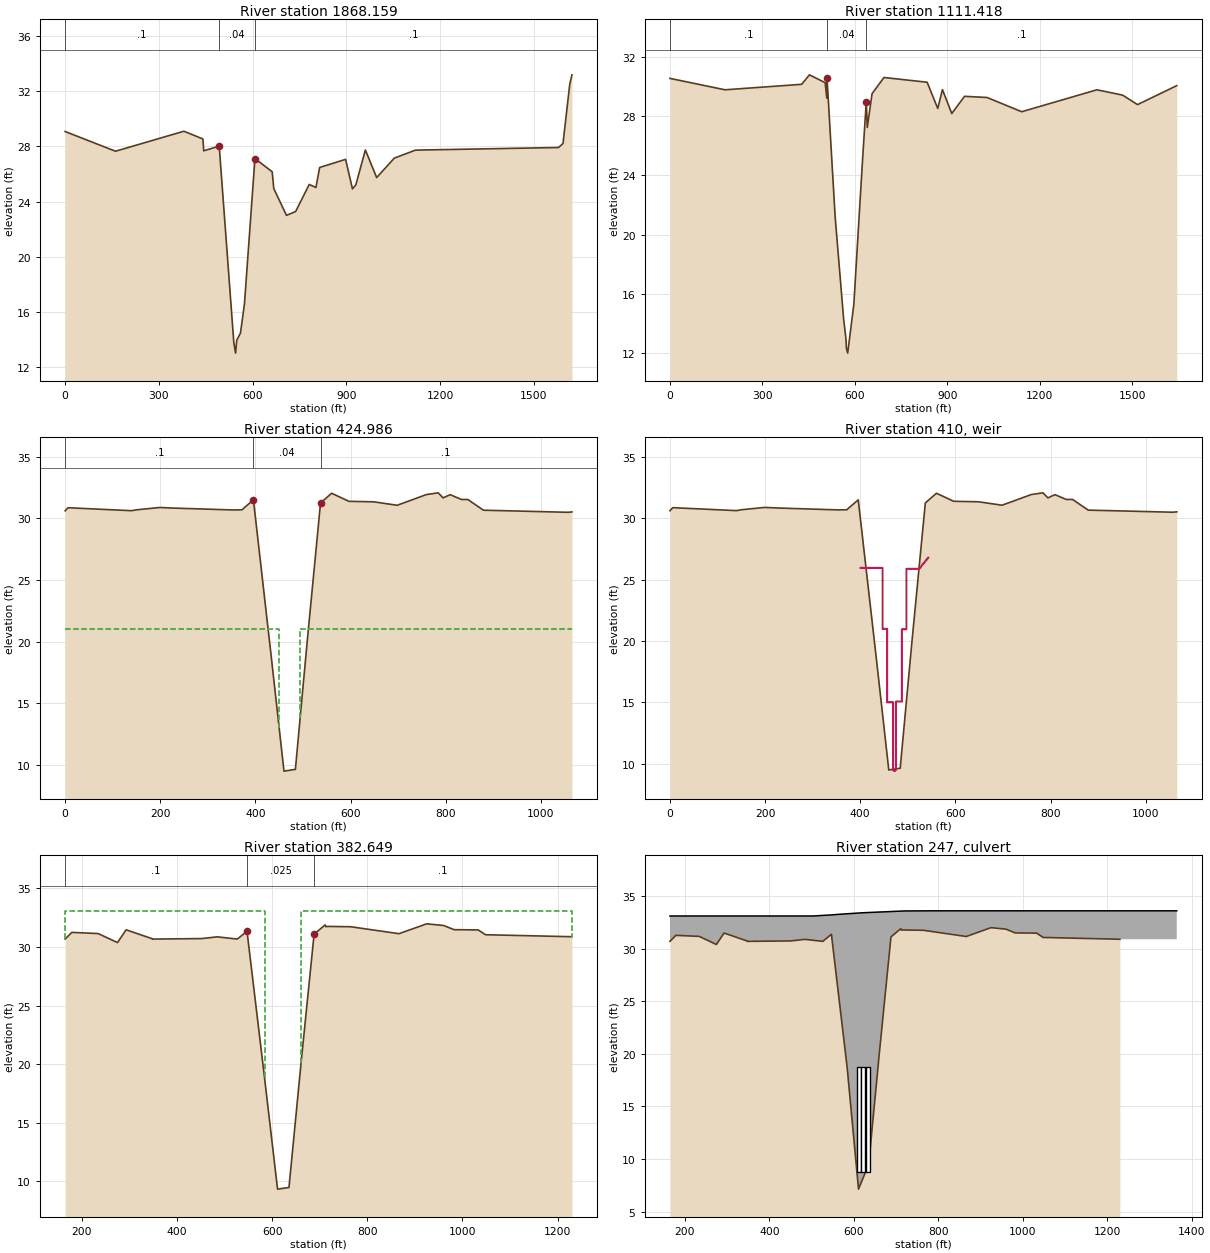
Type RM Length L Ch R = 1 ,1868.159,759.41,756.74,744.26
BEGIN DESCRIPTION:
462v1
Bank Station offset =      4454
END DESCRIPTION:
XS GIS Cut Line= 6
     3220667.359    13858611.188     3220837.708    13859017.898
     3220799.512    13859110.673     3220772.703     13859157.89
      3220731.24    13859262.776   3220192.9621313860001.0121334
#Sta/Elev= 30
       0   29.08   161.2   27.65  379.97    29.1  440.94   28.54  443.61   27.68
  493.11   28.02  539.85   13.79  545.58   13.01   549.3   13.95  561.16   14.46
  573.97    16.6  607.46   27.12  662.71   26.16  667.78   24.94  708.38      23
  737.79   23.28  781.19   25.24  802.67   25.02  814.47   26.47  897.55   27.06
   919.6   24.92  930.44   25.22  960.86   27.74  997.03   25.74 1053.48   27.15
 1121.18   27.73 1578.99   27.92 1593.37   28.21 1614.84   32.49    1622   33.19
#Mann= 3 , 0 , 0
       0      .1       0  493.11     .04       0  607.46      .1       0
Bank Sta=493.11,607.46
XS Rating Curve= 0
Exp/Cntr=.3,.1

Type RM Length L Ch R = 1 ,1111.418,686.01,686.43,687.32
BEGIN DESCRIPTION:
462v2
Bank Station offset =      4424
END DESCRIPTION:
XS GIS Cut Line= 6
     3220133.261    13858548.911     3220076.813    13858946.592
     3220044.587    13859160.735     3220025.876    13859267.806
     3219942.697    13859723.457 3219669.498973313860085.7529922
#Sta/Elev= 30
       0   30.55  178.43   29.78   427.4   30.15  452.47   30.79  503.39   30.26
   508.8   29.22  509.57   30.56  535.77   21.23  563.38    14.3  569.73    13.2
  571.53   12.76  572.25   12.34   576.5   12.01  596.46    15.3  624.03   24.82
  636.82   28.98  640.01   27.24  655.58   29.52  694.26   30.61  834.19   30.29
  868.61   28.52  883.86   29.79  914.14   28.18  955.45   29.34 1028.47   29.26
 1140.96    28.3 1384.95   29.78  1468.4   29.42 1516.59   28.78 1643.85   30.06
#Mann= 3 ,-1 , 0
       0      .1       0  509.57     .04       0  636.82      .1       0
Bank Sta=509.57,636.82
XS Rating Curve= 0
Exp/Cntr=.5,.3

Type RM Length L Ch R = 1 ,424.986 ,42.64,42.34,42.12
BEGIN DESCRIPTION:
Copy of 462s1u - xsec 4/4 of South Main st.
Bank Station offset =      4540
Channel inverts adjusted based on the slope between RS 1111.418 and RS 382.649
END DESCRIPTION:
XS GIS Cut Line= 6
     3219494.209    13858546.357     3219396.153    13858940.484
     3219391.141    13858962.658     3219373.186    13859032.135
     3219359.915    13859079.753     3219233.279    13859579.203
#Sta/Elev= 29
       0   30.62    6.02   30.87  139.65   30.63  149.89    30.7  199.03   30.89
  228.95   30.84   319.6   30.73     353   30.69  371.98    30.7   375.5  30.835
   395.8  31.505  433.23  18.795     460   9.495  483.99   9.635  509.36  20.235
  536.82  31.255  560.16  32.045  596.58   31.39  648.66   31.35  698.01   31.07
  759.47   31.94  784.16   32.08  794.49   31.67  809.32   31.93  833.03   31.54
  846.44   31.54  879.28   30.67 1057.36    30.5 1065.32   30.53
#Mann= 3 ,-1 , 0
       0      .1       0   395.8     .04       0  536.82      .1       0
#XS Ineff= 2 , 0
       0     450   20.99     494       0   20.99
Permanent Ineff=
       F       F
Bank Sta=395.8,536.82
XS Rating Curve= 0
Exp/Cntr=.5,.3

Type RM Length L Ch R = 5 ,410     ,,,
BEGIN DESCRIPTION:
Sheet pile transition drop structure 462s2, modeled as weir....Data from 1996 Costello LOMR. Elevations adjusted 0.5' for subsidence.
END DESCRIPTION:
IW Pilot Flow=0
#Inline Weir SE= 17
     401   25.96     420   25.96     447   25.96     447   20.99   456.5   20.99
   456.5   15.01     469   15.01     469     9.5     472     9.4     475     9.5
     475   15.07   487.5   15.07   487.5   20.96     497   20.96     497   25.89
     524   25.89     543    26.8
IW Dist,WD,Coef,Skew,MaxSub,Min_El,Is_Ogee,SpillHt,DesHd
14,2,3,0,.95,, 0 ,,,0,0,

Type RM Length L Ch R = 1 ,382.649 ,272.79,271.4,269.83
BEGIN DESCRIPTION:
462s1u - xsec 3/4 of South Main st.
Bank Station offset =      4553
Channel manning's n increased from 0.015 to consider the sheet pile wall u/s of the culvert
Channel in this area concrete lined.
END DESCRIPTION:
XS GIS Cut Line= 6
     3219452.671    13858538.583     3219351.526    13858946.327
     3219331.648     13859024.36     3219318.377    13859071.979
     3219191.741    13859571.428 3219191.738569913859571.4375844
#Sta/Elev= 30
  164.77   30.68   178.8   31.25  234.15   31.15  274.82   30.38  292.98   31.47
  347.11   30.72  348.21   30.67  349.11   30.68  451.35   30.72  484.37   30.87
  526.78   30.68  547.08   31.35  584.51   18.64  611.28    9.34  635.27    9.48
  660.64   20.08   688.1    31.1  711.44   31.89  712.48   31.75  714.84   31.75
  717.63   31.76   750.7   31.74  765.27   31.73  866.42   31.14  924.84   31.98
  960.32   31.84  982.44   31.48 1033.05   31.46 1048.41   31.05 1230.09   30.88
#Mann= 3 ,-1 , 0
  164.77      .1       0  547.08    .025       0   688.1      .1       0
#XS Ineff= 2 , 0
  164.77  584.51   33.09  660.64  164.77   33.09
Permanent Ineff=
       F       F
Bank Sta=547.08,688.1
XS Rating Curve= 0
Exp/Cntr=.5,.3

Type RM Length L Ch R = 2 ,247     ,,,
BEGIN DESCRIPTION:
South Main street. 3 Box culvert.
Internal sections: Channel inverts modified to represent the slope (as per PMT comments).
Internal sections are located on either side of the deck which is 45' wide and located at the center of the culvert. However the culvert inverts shown here (in the figure) are at the u/s and d/s end of the culvert. hence the culvert inverts appears to be lower than the channel invert on the d/s side, which is not the case.
END DESCRIPTION:
Bridge Culvert--1,0,-1,-1, 0
Deck Dist Width WeirC Skew NumUp NumDn MinLoCord MaxHiCord MaxSubmerge Is_Ogee
113,45,2.6,0, 8, 8, , , .95, 0, 0,0,,
  164.77  503.71  542.62  579.83  622.77  721.39  783.93 1364.77
   33.09   33.09   33.18   33.29    33.4   33.57   33.58   33.58
                                                                
       0  502.94  541.85  579.06     622  720.62  783.16    1250
   33.09   33.09   33.18   33.29    33.4   33.57   33.58   33.58
                                                                
Multiple Barrel Culv=2,10,10,201,.015,.5,1,8,2,8.72,4.69, 3,S Main St   , 0 ,35
  611.77  601.53  622.77  612.53  633.77  623.53
Culvert Bottom n=.015
BR U #Sta/Elev= 30
  164.77   30.68   178.8   31.25  234.15   31.15  274.82   30.38  292.98   31.47
  347.11   30.72  348.21   30.67  349.11   30.68  451.35   30.72  484.37   30.87
  526.78   30.68  547.08   31.35  584.51   18.64  611.28    7.14  635.27    9.48
  660.64   20.08   688.1    31.1  711.44   31.89  712.48   31.75  714.84   31.75
  717.63   31.76   750.7   31.74  765.27   31.73  866.42   31.14  924.84   31.98
  960.32   31.84  982.44   31.48 1033.05   31.46 1048.41   31.05 1230.09   30.88
BR U #Mann= 3
  164.77      .1  547.08    .015   688.1      .1
BR D #Sta/Elev= 65
       0   31.65   40.24   31.72   53.06   31.72   56.34   31.71   63.11   30.76
   81.16   29.09   82.12   28.79  108.04    19.6  115.75    18.8  128.13   18.71
  130.34   19.09  131.69   19.32  143.59   21.48  152.87   25.89  167.75   29.38
  185.08    30.7  191.04   30.62  192.73   30.62  270.29   30.57  300.84   30.78
  317.62   30.57  335.97   30.47  359.19    31.4   376.7   31.65   403.3   31.51
  405.22   31.44  407.31   31.27  431.88   28.86   442.5   28.85  457.38   29.78
  466.37   30.34  497.86   31.02  501.63    31.3  518.45   18.98  546.06      14
  580.73   11.74  583.77   12.66  583.94    6.23  611.28    6.23  641.82    6.23
  641.85    12.6   644.9   12.62  665.69   16.37  683.28   17.53   707.8   17.11
   716.7    31.6  735.39   32.76  755.02   32.79  812.88   32.76  830.23   32.75
  871.82   32.66  929.55   31.93  944.43   32.14  954.92    31.9   963.3   30.97
  982.92   30.36  991.15   29.94 1019.36    30.7 1034.02   32.09  1042.2   31.94
 1083.14   31.97 1123.03    32.1  1147.6   32.01 1160.21   32.29 1203.64   32.29
BR D #Mann= 3
       0      .1  501.63    .015   716.7      .1
BC Design=,, 0 ,, 0 ,,,,,,

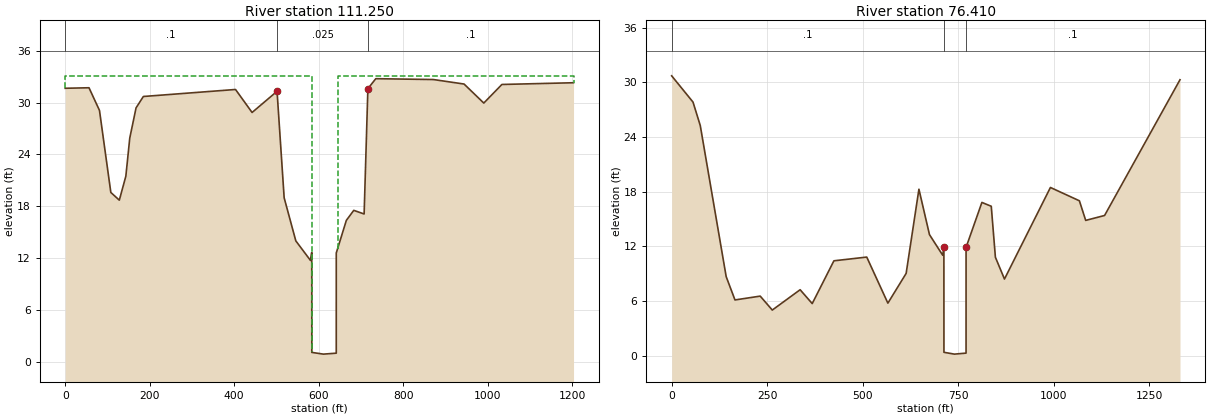
Type RM Length L Ch R = 1 ,111.250 ,34.76,34.84,34.72
BEGIN DESCRIPTION:
462v3 - xsec 2/4 of South Main st.
Bank Station offset =      4389
Channel Manning's n increased to consider baffle blocks downstream of the culvert
END DESCRIPTION:
XS GIS Cut Line= 6
 3219237.2804994 13858347.449006     3219182.847    13858471.787
       3219085.8     13858887.63     3219080.303    13858917.508
     3219066.139    13858977.753 3218940.109453313859511.7057871
#Sta/Elev= 30
       0   31.65   56.34   31.71   81.16   29.09  108.04    19.6  128.13   18.71
  143.59   21.48  152.87   25.89  167.75   29.38  185.08    30.7   403.3   31.51
   442.5   28.85  501.63    31.3  518.45   18.98  546.06      14  580.73   11.74
  583.77   12.66  583.94     1.1  611.28      .9  641.82    1.01  641.85    12.6
  665.69   16.37  683.28   17.53   707.8   17.11   716.7    31.6  735.39   32.76
  871.82   32.66  944.43   32.14  991.15   29.94 1034.02   32.09 1203.64   32.29
#Mann= 3 ,-1 , 0
       0      .1       0  501.63    .025       0   716.7      .1       0
#XS Ineff= 2 , 0
       0  583.94   33.09   644.9       0   33.09
Permanent Ineff=
       F       F
Bank Sta=501.63,716.7
XS Rating Curve= 0
Exp/Cntr=.5,.3

Type RM Length L Ch R = 1 ,76.410  ,114.69,76.41,115.64
BEGIN DESCRIPTION:
Copy of 462v3 - xsec 1/4 of South Main st.
Bank Station offset =   4259
ROB and LOB reach lengths greater than that of channel since this is the most d/s cross section.
Channel inverts adjusted based on the u/s and d/s inverts of the culvert.
END DESCRIPTION:
XS GIS Cut Line= 6
     3219257.959    13858233.435     3219180.521    13858359.365
     3219148.831    13858465.465     3219051.065    13858884.385
     3219031.404    13858974.508      3218905.17    13859509.326
#Sta/Elev= 30
       0   30.71   55.87   27.83   74.85   25.26  142.65     8.7  165.69    6.14
  231.75    6.56  263.34    5.03  336.23    7.26  367.89    5.74  424.64   10.43
  510.61   10.84   565.9    5.79  613.72    9.05  647.17   18.28  674.78    13.3
  709.45   11.04  712.49   11.96  712.66      .4     740      .2  770.54     .31
  770.57    11.9     812   16.83  836.52   16.41  847.35   10.82   871.1    8.43
  991.37   18.47 1067.19   17.01 1083.71   14.86 1133.11    15.4 1330.52   30.28
#Mann= 3 , 0 , 0
       0      .1       0  712.49    .015       0  770.57      .1       0
Bank Sta=712.49,770.57
XS Rating Curve= 0
Exp/Cntr=.3,.1

Chan Stop Cuts=-1